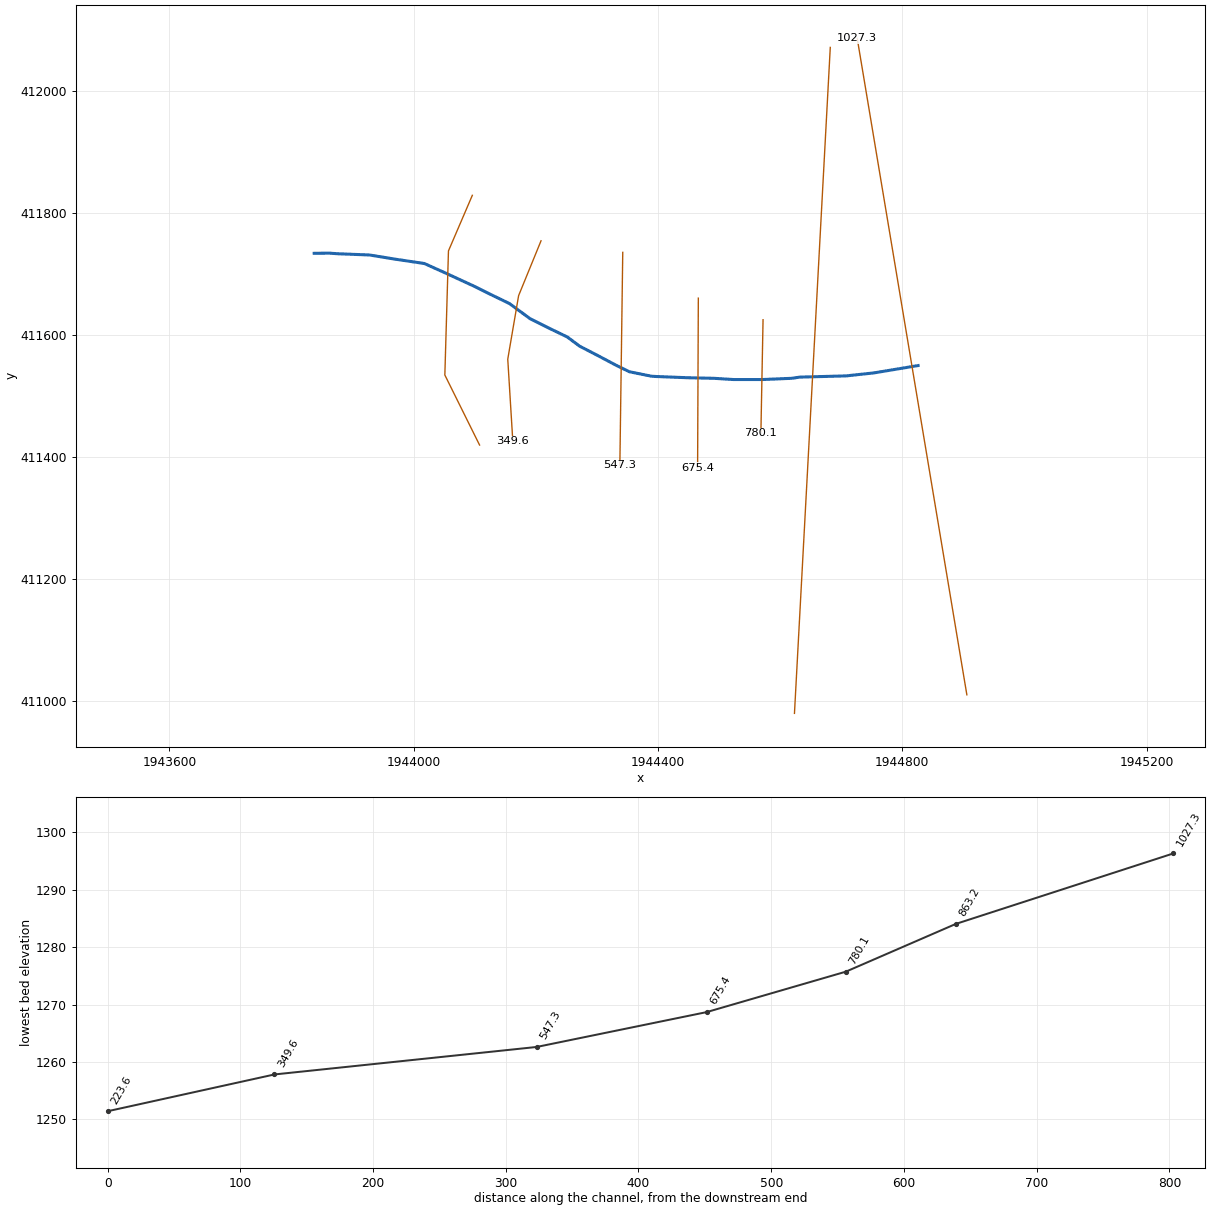
--- ShadeCrk.prj (project) ---

Proj Title=ShadeCrk
Current Plan=p01
Geom File=g01
Flow File=f01
Plan File=p01
DSS Export Rating Curves=0
DSS Export Rating Curve Sorted=0
DSS Export Volume Flow Curves=0
DXF OffsetX=0
DXF OffsetY=0
DXF ScaleX=0
DXF ScaleY=0

--- ShadeCrk.p01 (plan) ---

Plan Title=Floodplain
Program Version=4.00
Geom File=g01
Flow File=f01
K Sum by GR=0
Std Step Tol=0.01
Critical Tol=0.01
Num of Std Step Trials=20
Max Error Tol=0.3
Flow Tol Ratio=0.001
Split Flow NTrial=30
Split Flow Tol=0.02
Split Flow Ratio=0.02
Log Output Level=0
Friction Slope Method=1
Unsteady Friction Slope Method=2
Unsteady Bridges Friction Slope Method=1
Global Log Level=0
CheckData=False
Run HTab=0
Run UNet=0
Run PostProcess=0
UNET Theta=0
UNET Theta Warmup=0
UNET ZTol=0
UNET ZSATol=0
UNET MxIter=0
UNET MaxInSteps=0
UNET DtIC=0
UNET DtMin=0
UNET MaxCRTS=0
UNET WFStab=0
UNET SFStab=0
UNET WFX=0
UNET SFX=0
UNET DSS MLevel=0
UNET DZMax Abort=0
UNET Convert EG Bridges=0
UNET Use Existing IB Tables=0
UNET Froude Limit=0
UNET Froude Power=0
Write IC File=0
Echo Input=False
Echo Output=False
Write Detailed=0

--- ShadeCrk.f01 (steady flow) ---

Flow Title=NFF Regression Equation
Program Version=4.00
Number of Profiles=1
Profile Names=P100yr
River Rch & RM=ShadeCrk,Main      ,1027.3
516.8381
River Rch & RM=ShadeCrk,Main      ,223.6
531.3922
Boundary for River Rch & Prof#=ShadeCrk,Main      ,1
Up Type=0
Dn Type=3
Dn Slope=0.040428

--- ShadeCrk.g01 (geometry) ---

Geom Title=USGS 3m DEM
Program Version=4.00

River Reach=ShadeCrk     ,Main
Reach XY= 28
     1944825.920      411549.636     1944754.141      411537.673
     1944708.283      411532.689     1944632.517      411530.695
     1944618.560      411528.701     1944570.708      411526.707
     1944523.852      411526.707     1944491.950      411528.701
     1944448.086      411529.698     1944397.243      411531.692
     1944389.330      411532.186     1944353.432      411539.459
     1944332.443      411549.636     1944300.541      411566.584
     1944271.631      411581.538     1944251.692      411596.492
     1944220.788      411611.446     1944190.880      411626.399
     1944156.985      411651.322     1944120.098      411669.267
     1944098.166      411680.233     1944046.326      411704.159
     1944017.415      411717.120     1943970.560      411724.098
     1943927.692      411731.076     1943876.849      411733.070
     1943861.895      411734.067     1943837.214      411733.825

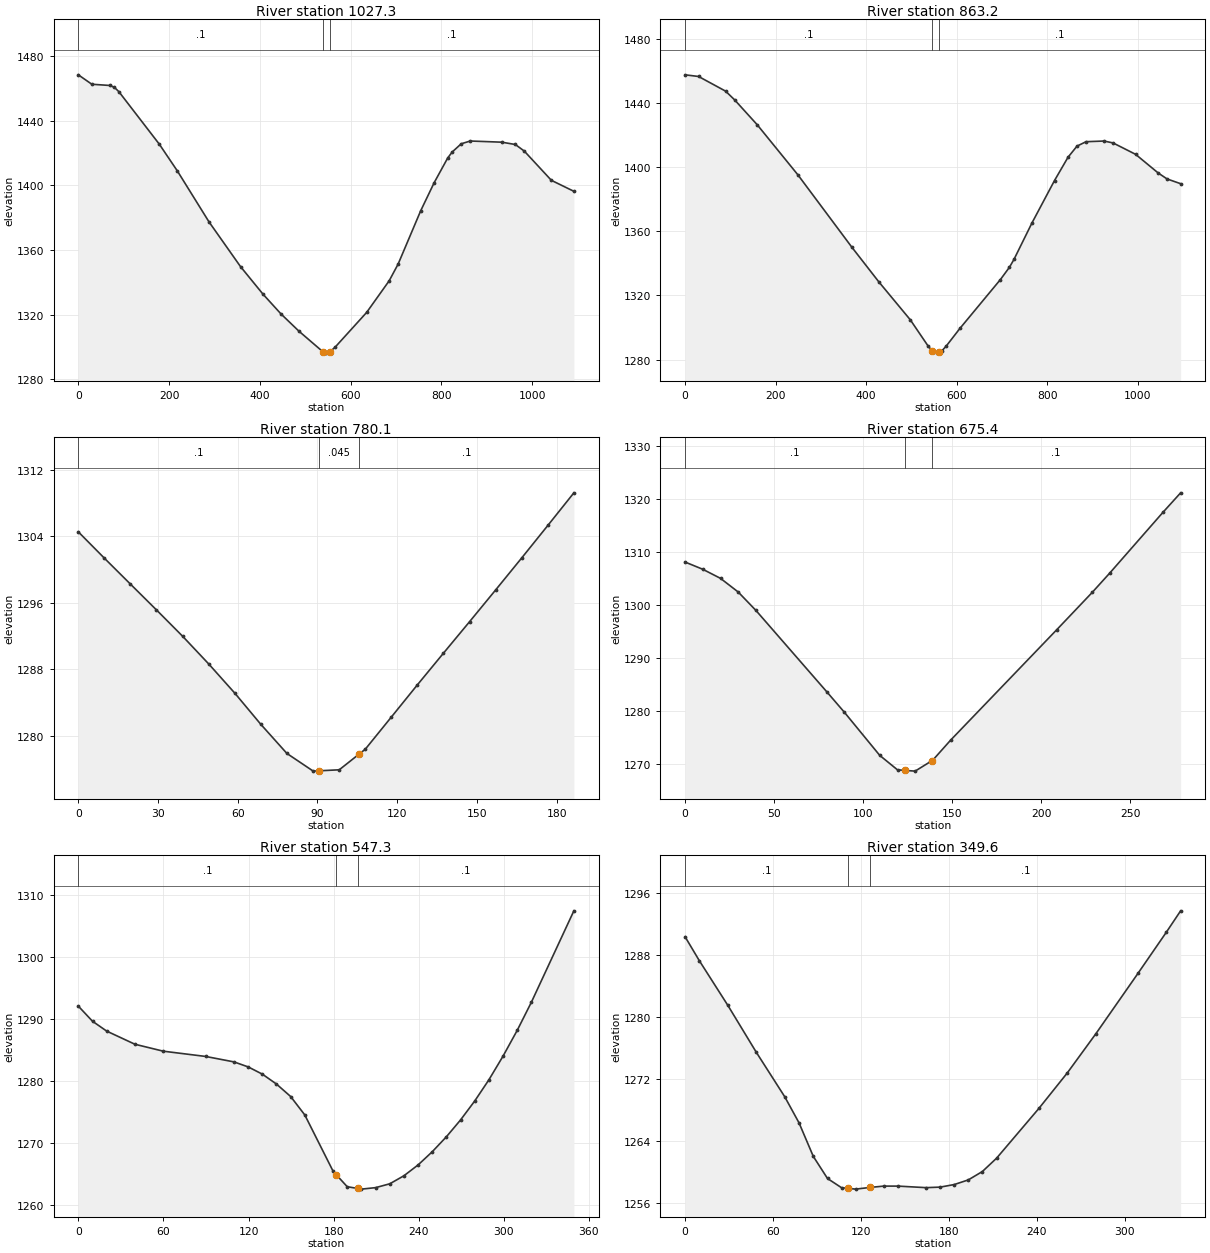
Type RM Length L Ch R = 1 ,1027.3,168.9,164,159.1
XS GIS Cut Line= 3
     1944905.816      411009.421     1944816.056      411547.992
     1944726.295      412086.564
#Sta/Elev= 30
       0 1468.25    29.8 1462.43    69.5 1461.67    79.4 1460.54    89.4 1457.83
   178.7 1425.31   218.4 1408.79   287.9 1377.42   357.4 1349.76   407.0 1332.71
   446.7 1320.48   486.4 1309.79   538.5 1297.25   546.0 1296.29   553.5 1296.93
   565.8 1299.94   635.4 1321.46   685.0 1340.99   704.8 1351.36   754.5 1384.28
   784.2 1401.64   814.0 1416.89   824.0 1420.60   843.8 1425.64   863.7 1427.36
   933.2 1426.63   963.0 1425.20   982.8 1421.11  1042.4 1403.06  1092.0 1396.28
#Mann= 3 , 0 , 0
       0     0.1       0   538.5   0.045       0   553.5     0.1       0
Bank Sta=   538.5,   553.5
Exp/Cntr=0.3,0.1

Type RM Length L Ch R = 1 ,863.2,82.2,82.9,83.7
XS GIS Cut Line= 2
     1944623.539      410978.947     1944682.183      412071.669
#Sta/Elev= 30
       0 1457.54    29.8 1456.51    89.5 1447.36   109.4 1441.93   159.2 1426.44
   248.7 1395.33   368.1 1350.12   427.8 1328.47   497.4 1304.77   537.2 1288.22
   545.6 1285.48   557.1 1284.02   560.6 1284.51   567.0 1285.40   577.0 1288.54
   606.8 1299.39   696.4 1329.92   716.3 1337.57   726.2 1342.42   766.0 1365.19
   815.8 1391.64   845.6 1406.14   865.5 1413.10   885.4 1415.84   925.2 1416.26
   945.1 1415.07   994.8 1407.98  1044.6 1396.37  1064.4 1392.61  1094.3 1389.66
#Mann= 3 , 0 , 0
       0     0.1       0   545.6   0.045       0   560.6     0.1       0
Bank Sta=   545.6,   560.6
Exp/Cntr=0.3,0.1

Type RM Length L Ch R = 1 ,780.1,104.4,104.8,105.1
XS GIS Cut Line= 2
     1944572.114      411624.844     1944568.562      411438.340
#Sta/Elev= 22
       0 1304.53     9.8 1301.36    19.6 1298.24    29.4 1295.13    39.3 1291.94
    49.1 1288.61    58.9 1285.10    68.7 1281.34    78.5 1277.84    88.4 1275.71
    90.7 1275.75    98.2 1275.87   105.7 1277.77   108.0 1278.35   117.8 1282.22
   127.6 1286.10   137.4 1289.91   147.3 1293.73   157.1 1297.55   166.9 1301.40
   176.7 1305.30   186.5 1309.23
#Mann= 3 , 0 , 0
       0     0.1       0    90.7   0.045       0   105.7     0.1       0
Bank Sta=    90.7,   105.7
Exp/Cntr=0.3,0.1

Type RM Length L Ch R = 1 ,675.4,127.7,128.2,128.8
XS GIS Cut Line= 2
     1944466.132      411660.220     1944464.948      411381.945
#Sta/Elev= 19
       0 1308.16     9.9 1306.80    19.9 1305.08    29.8 1302.51    39.8 1299.02
    79.5 1283.69    89.4 1279.82   109.3 1271.66   119.3 1268.92   123.4 1268.82
   129.2 1268.68   138.4 1270.60   139.1 1270.75   149.1 1274.52   208.7 1295.37
   228.6 1302.41   238.5 1306.08   268.3 1317.52   278.3 1321.23
#Mann= 3 , 0 , 0
       0     0.1       0   123.4   0.045       0   138.4     0.1       0
Bank Sta=   123.4,   138.4
Exp/Cntr=0.3,0.1

Type RM Length L Ch R = 1 ,547.3,201,197.5,193.2
XS GIS Cut Line= 2
     1944342.389      411735.414     1944337.652      411386.089
#Sta/Elev= 30
       0 1292.13    10.0 1289.69    20.0 1288.10    39.9 1285.98    59.9 1284.86
    89.8 1284.01   109.8 1283.13   119.8 1282.32   129.8 1281.15   139.7 1279.56
   149.7 1277.55   159.7 1274.57   179.7 1265.47   181.9 1264.92   189.6 1263.00
   196.9 1262.72   199.6 1262.61   209.6 1262.85   219.6 1263.47   229.6 1264.77
   239.6 1266.52   249.5 1268.63   259.5 1271.05   269.5 1273.77   279.5 1276.83
   289.5 1280.25   299.4 1284.04   309.4 1288.20   319.4 1292.74   349.4 1307.50
#Mann= 3 , 0 , 0
       0     0.1       0   181.9   0.045       0   196.9     0.1       0
Bank Sta=   181.9,   196.9
Exp/Cntr=0.3,0.1

Type RM Length L Ch R = 1 ,349.6,122.9,125.7,129.4
XS GIS Cut Line= 4
     1944208.579      411754.360     1944171.871      411664.365
     1944154.108      411560.159     1944162.397      411425.166
#Sta/Elev= 26
       0 1290.36     9.7 1287.28    29.2 1281.51    48.6 1275.47    68.0 1269.74
    77.8 1266.36    87.5 1262.05    97.2 1259.20   106.8 1258.01   111.3 1257.93
   116.4 1257.83   126.3 1258.05   135.6 1258.22   145.2 1258.22   164.5 1258.02
   174.1 1258.09   183.7 1258.42   193.3 1259.02   202.9 1260.10   212.6 1261.82
   241.5 1268.24   260.9 1272.82   280.2 1277.82   309.2 1285.67   328.5 1290.96
   338.2 1293.70
#Mann= 3 , 0 , 0
       0     0.1       0   111.3   0.045       0   126.3     0.1       0
Bank Sta=   111.3,   126.3
Exp/Cntr=0.3,0.1

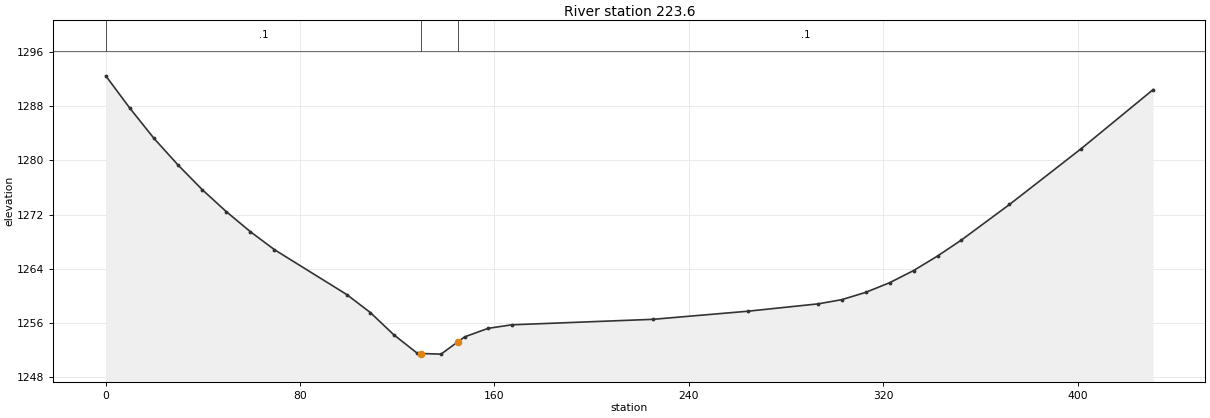
Type RM Length L Ch R = 1 ,223.6,224.4,223.8,223.3
XS GIS Cut Line= 4
     1944096.085      411828.962     1944057.008      411737.782
     1944051.087      411534.108     1944107.926      411419.245
#Sta/Elev= 30
       0 1292.44     9.9 1287.68    19.8 1283.24    29.8 1279.28    39.7 1275.67
    49.6 1272.43    59.5 1269.48    69.4 1266.83    99.2 1260.21   108.9 1257.56
   118.6 1254.27   128.3 1251.54   129.8 1251.52   138.0 1251.43   144.8 1253.21
   147.7 1253.97   157.4 1255.23   167.1 1255.75   225.3 1256.56   264.2 1257.75
   293.3 1258.84   303.0 1259.46   312.8 1260.53   322.7 1261.96   332.5 1263.74
   342.4 1265.89   352.2 1268.24   372.0 1273.48   401.5 1281.70   431.1 1290.40
#Mann= 3 , 0 , 0
       0     0.1       0   129.8   0.045       0   144.8     0.1       0
Bank Sta=   129.8,   144.8
Exp/Cntr=0.3,0.1